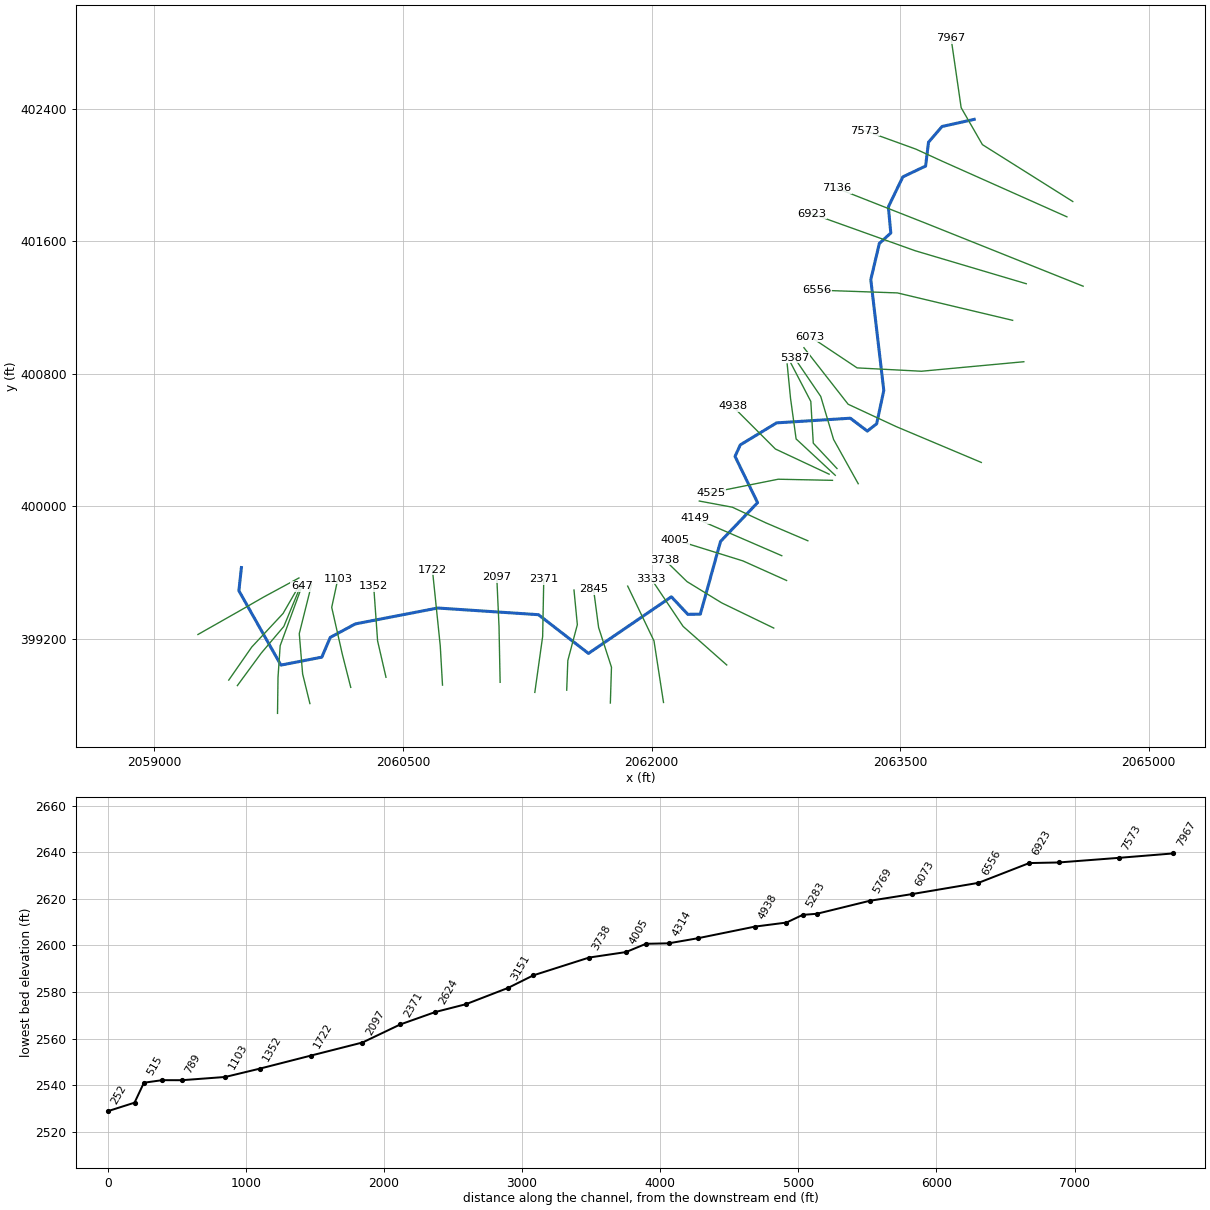
--- HOMINYCK.prj (project) ---

Proj Title=HOMINYCK
Current Plan=p01
Default Exp/Contr=0,0
English Units
Geom File=g01
Flow File=f01
Plan File=p01
BEGIN DESCRIPTION:
Stream Name- Hominy Creek
Flood Zone: Zone A
Greenbrier County, WV
County-Wide Study
WVDHSEM-2018-3, Flood Risk Project
HEC-RAS Version: 5.0.7
General Notes:
For the Hydrology Regression was used.
END DESCRIPTION:
DSS Export Rating Curves= 0
DSS Export Rating Curve Sorted= 0
DSS Export Volume Flow Curves= 0
DXF Filename=..\..\..\H1\Remaining\splitted_models\HOMINYCK\GRBRRVTR1.
DXF OffsetX= 0
DXF OffsetY= 0
DXF ScaleX= 0
DXF ScaleY= 0

--- HOMINYCK.p01 (plan) ---

Plan Title=Floodplain
Program Version=5.07
Short Identifier=Floodplain
Geom File=g01
Flow File=f01
Subcritical Flow
K Sum by GR= 0
Std Step Tol= 0.01
Critical Tol= 0.01
Num of Std Step Trials= 20
Max Error Tol= 0.3
Flow Tol Ratio= 0.001
Split Flow NTrial= 30
Split Flow Tol= 0.02
Split Flow Ratio= 0.02
Log Output Level= 0
Friction Slope Method= 1
Unsteady Friction Slope Method= 2
Unsteady Bridges Friction Slope Method= 1
Parabolic Critical Depth
Global Vel Dist= 0 , 0 , 0
Global Log Level= 0
CheckData=True
Encroach Param=-1 ,0,0, 0
Mapping Interval=1HOUR
Computation Time Step Use Courant=        0
Computation Time Step Use Time Series=    0
Computation Time Step Count To Double=0
Computation Time Step Max Doubling=0
Computation Time Step Max Halving=0
Computation Time Step Residence Courant=0
Run HTab= 0
Run UNet= 0
Run Sediment= 0
Run PostProcess= 0
Run WQNet= 0
Run RASMapper= 0
UNET Theta= 0
UNET Theta Warmup= 0
UNET ZTol= 0
UNET ZSATol= 0
UNET MxIter= 0
UNET Max Iter WO Improvement= 0
UNET MaxInSteps= 0
UNET DtIC= 0
UNET DtMin= 0
UNET MaxCRTS= 0
UNET WFStab= 0
UNET SFStab= 0
UNET WFX= 1
UNET SFX= 1
UNET 1D Methodology=Finite Difference
UNET DSS MLevel= 1
UNET Pardiso=0
UNET DZMax Abort= 0
UNET Use Existing IB Tables= 0
UNET Froude Reduction=False
UNET Froude Limit= 0
UNET Froude Power= 0
UNET D1 Cores= 0
UNET D2 Coriolis=0
UNET D2 Cores= 0
UNET D2 Theta= 1
UNET D2 Theta Warmup= 1
UNET D2 Z Tol= 0.01
UNET D2 Volume Tol= 0.01
UNET D2 Max Iterations= 20
UNET D2 Equation= 0
UNET D2 RampUpFraction=0.1
UNET D2 TimeSlices= 1
UNET D2 BCVolumeCheck=0
UNET D1D2 MaxIter= 0
UNET D1D2 ZTol=0.01
UNET D1D2 QTol=0.1
UNET D1D2 MinQTol=1
Write IC File= 0
Write IC File at Fixed DateTime=0
Write IC File at Sim End=0
Echo Input=False
Echo Parameters=False
Echo Output=False
Write Detailed= 0
HDF Write Warmup=0
HDF Write Time Slices=0
HDF Flush=0
HDF Face Node Velocities=0
HDF Compression= 1
HDF Chunk Size= 1
HDF Spatial Parts= 1
HDF Use Max Rows=0
HDF Fixed Rows= 1
Calibration Method= 0
Calibration Iterations= 20
Calibration Max Change=0.05
Calibration Tolerance=0.2
Calibration Maximum=1.5
Calibration Minimum=0.5
Calibration Optimization Method= 1
WQ AD Non Conservative
WQ ULTIMATE=-1
WQ Max Comp Step=1HOUR
WQ Output Interval=15MIN
WQ Output Selected Increments= 0
WQ Output face flow=0
WQ Output face velocity=0
WQ Output face area=0
WQ Output face dispersion=0
WQ Output cell volume=0
WQ Output cell surface area=0
WQ Output cell continuity=0
WQ Output cumulative cell continuity=0
WQ Output face conc=0
WQ Output face dconc_dx=0
WQ Output face courant=0
WQ Output face peclet=0
WQ Output face adv mass=0
WQ Output face disp mass=0
WQ Output cell mass=0
WQ Output cell source sink temp=0
WQ Output nsm pathways=0
WQ Output nsm derived pathways=0
WQ Output MaxMinRange=-1
WQ Daily Max Min Mean=-1
WQ Daily Range=0
WQ Daily Time=0
WQ Create Restart=0
WQ Fixed Restart=0
WQ System Summary=0
WQ Write To DSS=0
WQ Use Fixed Temperature=0
Sorting and Armoring Iterations= 10
XS Update Threshold= 0.02
Bed Roughness Predictor= 0
Hydraulics Update Threshold= 0.02
Energy Slope Method= 1
Volume Change Method= 1
Sediment Retention Method= 0
XS Weighting Method= 0
Number of US Weighted Cross Sections= 1
Number of DS Weighted Cross Sections= 1
Upstream XS Weight=0
Main XS Weight=1
Downstream XS Weight=0
Number of DS XS's Weighted with US Boundary= 1
Upstream Boundary Weight= 1
Weight of XSs Associated with US Boundary= 0
Number of US XS's Weighted with DS Boundary= 1
Downstream Boundary Weight= 0.5
Weight of XSs Associated with DS Boundary= 0.5
Percentile Method= 0
Sediment Output Level= 3
Mass or Volume Output= 0
Output Increment Type= 1
Profile and TS Output Increment= 1
XS Output Flag= 0
XS Output Increment= 10
Write Gradation File= 0
Read Gradation Hotstart= 0
Write HDF5 File= 1
Write Binary Output= 1
Write DSS Sediment File= 0
SV Curve= 0
Specific Gage Flag= 0

--- HOMINYCK.f01 (steady flow) ---

Flow Title=Flow
Program Version=5.07
Number of Profiles= 6
Profile Names=f1p,f10p,f4p,f2p,f02p,f1pplus
River Rch & RM=HOMINYCK,Main            ,7967
     529     279     371     448     740     622
River Rch & RM=HOMINYCK,Main            ,7136
     857     460     607     728    1190    1009
River Rch & RM=HOMINYCK,Main            ,4149
     967     521     687     822    1340    1138
River Rch & RM=HOMINYCK,Main            ,2371
    1170     637     836     998    1620    1377
Boundary for River Rch & Prof#=HOMINYCK,Main            , 1
Up Type= 0
Dn Type= 3
Dn Slope=0.01143
Boundary for River Rch & Prof#=HOMINYCK,Main            , 2
Up Type= 0
Dn Type= 3
Dn Slope=0.01143
Boundary for River Rch & Prof#=HOMINYCK,Main            , 3
Up Type= 0
Dn Type= 3
Dn Slope=0.01143
Boundary for River Rch & Prof#=HOMINYCK,Main            , 4
Up Type= 0
Dn Type= 3
Dn Slope=0.01143
Boundary for River Rch & Prof#=HOMINYCK,Main            , 5
Up Type= 0
Dn Type= 3
Dn Slope=0.01143
Boundary for River Rch & Prof#=HOMINYCK,Main            , 6
Up Type= 0
Dn Type= 3
Dn Slope=0.01143
DSS Import GetInterval= 0
DSS Import GetPeak= 0
DSS Import FillOption= 0

--- HOMINYCK.g01 (geometry) ---

Geom Title=Geometry
Program Version=5.07

River Reach=HOMINYCK        ,Main
Reach XY= 30
     2063946.562      402334.643     2063752.925      402291.736
     2063671.182      402196.968     2063653.607      402053.049
     2063516.105      401987.666     2063428.861      401806.597
     2063443.598      401649.314       2063374.4      401586.032
     2063322.943      401367.827     2063401.337      400699.441
     2063358.289      400498.048     2063301.955       400454.02
     2063199.488      400531.692     2062754.585       400503.56
     2062535.436      400370.657     2062503.854      400301.349
     2062639.829      400022.213       2062416.2      399788.055
     2062294.505      399349.514     2062218.968      399348.505
     2062119.879      399454.252     2061619.508      399112.655
2061317.72910569399346.3068108422060709.86912858399386.563381336
2060212.91791876399290.6605162842060061.79825262399209.288388361
2060010.94067267399090.1363439022059763.91814147399042.184911376
2059510.46438825399490.8406774732059525.69651095399630.604346854

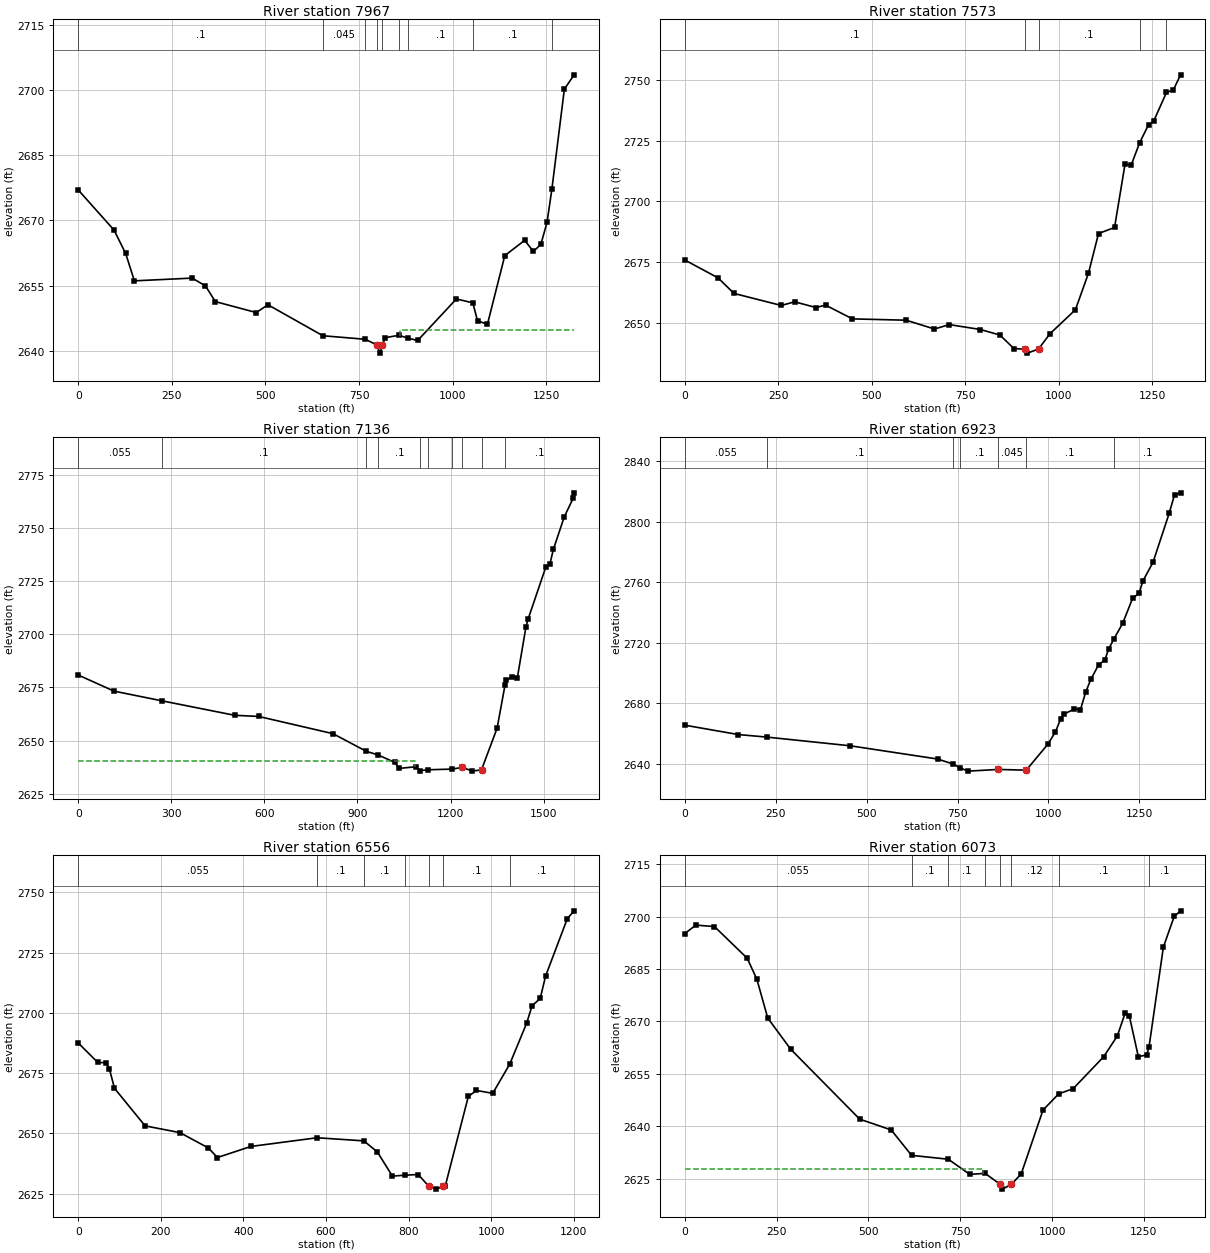
Type RM Length L Ch R = 1 ,7967    ,394.4,394.4,394.4
XS GIS Cut Line= 4
2064541.71236008401839.0066361992063996.36970563402182.189943501
2063868.09791209402404.9777954542063807.33758883402823.548911246
#Sta/Elev= 30
       0    2677    95.7 2667.77   126.7  2662.4     150 2656.11   304.4 2656.74
   339.9 2654.94   366.2 2651.34   475.6 2648.82   506.6 2650.62  653.442643.492
  766.942642.682  797.412641.372   805.8  2639.5  812.222641.371     820 2643.06
  857.032643.597  880.462642.923   906.7 2642.42  1009.9 2651.95 1053.832651.052
  1066.3 2646.95  1092.8 2646.12  1139.2 2661.91  1192.3 2665.42  1215.5 2662.86
  1235.4 2664.48    1252 2669.55 1264.912677.162  1298.3 2700.18  1324.4 2703.45
#Mann= 9 ,-1 , 0
       0      .1       0  653.44    .045       0  766.94      .1       0
  797.41    .045       0  812.22      .1       0  857.03    .045       0
  880.46      .1       0 1053.83      .1       0 1264.91      .1       0
#XS Ineff= 2 , 0
                          858.86         2644.77
Permanent Ineff=
       F       F
Bank Sta=797.41,812.22
XS Rating Curve= 0 ,0
Exp/Cntr(USF)=0,0
Exp/Cntr=0.3,0.1

Type RM Length L Ch R = 1 ,7573    ,437.1,437.1,437.1
XS GIS Cut Line= 4
2064506.08130632401746.7409601372063756.70398611402080.922738067
2063594.67645742402155.185355385 2063287.4992676402266.579281362
#Sta/Elev= 30
       0 2675.91    89.2 2668.54   131.8 2662.14   258.1  2657.2     294 2658.69
   350.8 2656.35   376.6 2657.33   448.4 2651.68   592.1 2651.13   667.6 2647.51
   707.1 2649.33   790.5 2647.31   842.6 2645.03   879.8  2639.5   909.4 2639.19
   915.9  2637.6  945.712639.286   976.2 2645.55  1044.3 2655.42  1079.1  2670.4
  1106.1 2686.77  1148.9 2689.25  1176.9 2715.29  1193.2 2714.82 1215.942724.067
  1239.7 2731.48  1253.6    2733 1287.632744.759    1306 2745.81  1325.5 2752.01
#Mann= 5 ,-1 , 0
       0      .1       0   909.4    .045       0  945.71      .1       0
 1215.94      .1       0 1287.63      .1       0
Bank Sta=909.4,945.71
XS Rating Curve= 0 ,0
Exp/Cntr(USF)=0,0
Exp/Cntr=0.3,0.1

Type RM Length L Ch R = 1 ,7136    ,212.5,212.5,212.5
XS GIS Cut Line= 3
2064603.97293824401328.1698443462063641.93448662401712.985224993
2063118.72059188401918.895209374
#Sta/Elev= 30
       0 2680.85   115.4 2673.26  270.972668.667   503.8  2661.9   581.9 2661.34
   821.1 2653.24  928.032644.976  967.392643.168    1020 2639.73  1034.2 2636.89
  1087.3 2637.65 1103.172635.868 1126.132636.239 1204.82 2636.57  1238.4 2637.36
  1270.4 2635.61 1299.792636.235  1350.1 2655.83 1375.622676.149  1379.7 2678.28
  1397.3 2679.96    1415 2679.27  1443.2 2703.63  1450.2 2707.26  1506.6 2731.47
  1520.7 2733.32  1531.3 2739.95  1566.6  2755.3  1594.8 2763.94  1598.4  2766.6
#Mann= 10 ,-1 , 0
       0    .055       0  270.97      .1       0  928.03    .055       0
  967.39      .1       0 1103.17      .1       0 1126.13      .1       0
 1204.82      .1       0  1238.4    .045       0 1299.79      .1       0
 1375.62      .1       0
#XS Ineff= 2 , 0
         1085.68  2640.3
Permanent Ineff=
       F       F
Bank Sta=1238.4,1299.79
XS Rating Curve= 0 ,0
Exp/Cntr(USF)=0,0
Exp/Cntr=0.3,0.1

Type RM Length L Ch R = 1 ,6923    ,367.6,367.6,367.6
XS GIS Cut Line= 3
2064260.83974813401343.0494414992063589.83902942401542.356585672
2062965.34331101 401766.02349191
#Sta/Elev= 30
       0  2665.7   147.5 2659.49   226.2 2657.81   455.5 2652.07   695.1 2643.36
   736.5 2640.16   757.7 2637.47   778.6 2635.36   862.3 2636.47   938.9 2635.99
   998.2 2653.09  1019.1  2661.2  1034.1 2670.07  1041.8 2672.89  1071.3 2676.36
    1088 2676.01  1102.7 2687.76  1116.6 2695.93  1137.6 2705.42    1155 2708.73
  1165.4 2715.95  1180.4 2722.82  1203.8 2732.79  1231.6 2749.58  1249.1 2752.68
  1259.5  2760.8  1287.4 2773.18  1331.8 2805.48  1346.6 2817.78  1363.3 2819.03
#Mann= 7 ,-1 , 0
       0    .055       0   226.2      .1       0   736.5    .055       0
   757.7      .1       0   862.3    .045       0   938.9      .1       0
  1180.4      .1       0
Bank Sta=862.3,938.9
XS Rating Curve= 0 ,0
Exp/Cntr(USF)=0,0
Exp/Cntr=0.3,0.1

Type RM Length L Ch R = 1 ,6556    ,482.7,482.7,482.7
XS GIS Cut Line= 3
2064178.65067541401122.2598599642063483.28253144401287.662962172
2062997.19994536401304.540829744
#Sta/Elev= 30
       0  2687.5    47.3 2679.42    67.6 2679.29    75.6 2676.71    87.8  2668.7
     162 2653.11   246.3 2650.31   315.3 2643.94   337.1 2639.98   418.3 2644.57
  578.482648.177  691.722646.889   724.3 2642.33     761 2632.26  791.732632.661
   823.4 2632.92  848.872628.066   867.1 2626.87  884.112628.066     889 2628.21
   944.8  2665.3   964.5  2667.8  1003.9  2666.6 1045.282678.785    1086 2695.68
  1099.1 2702.87  1118.9 2705.99    1132 2715.28  1184.5 2739.04  1201.1  2742.3
#Mann= 7 ,-1 , 0
       0    .055       0  578.48      .1       0  691.72      .1       0
  791.73      .1       0  848.87    .045       0  884.11      .1       0
 1045.28      .1       0
Bank Sta=848.87,884.11
XS Rating Curve= 0 ,0
Exp/Cntr(USF)=0,0
Exp/Cntr=0.3,0.1

Type RM Length L Ch R = 1 ,6073    ,303.7,303.7,303.7
XS GIS Cut Line= 4
 2064246.1621457400872.4674198952063628.43219256 400815.08267015
 2063240.2412384400835.3361112362062956.69306318401024.368228045
#Sta/Elev= 30
       0 2695.11    30.7 2697.55    81.1 2697.12   170.1 2688.08   196.4 2682.09
   226.1 2670.96   288.7 2662.03   476.5 2642.04   562.2 2638.96  617.632631.687
  717.632630.582   775.9 2626.25  817.552626.542  859.53 2623.36   864.6 2622.03
  888.912623.362     916 2626.38   975.3 2644.64 1018.152649.292  1057.4 2650.76
  1140.2 2659.87  1177.5 2665.81  1199.3 2672.51  1210.2 2671.61  1234.8 2659.94
  1257.5 2660.39 1263.772662.605    1303 2691.28  1332.5 2700.04  1349.9 2701.63
#Mann= 8 ,-1 , 0
       0    .055       0  617.63      .1       0  717.63      .1       0
  817.55     .12       0  859.53    .045       0  888.91     .12       0
 1018.15      .1       0 1263.77      .1       0
#XS Ineff= 2 , 0
          811.32 2627.79
Permanent Ineff=
       F       F
Bank Sta=859.53,888.91
XS Rating Curve= 0 ,0
Exp/Cntr(USF)=0,0
Exp/Cntr=0.3,0.1

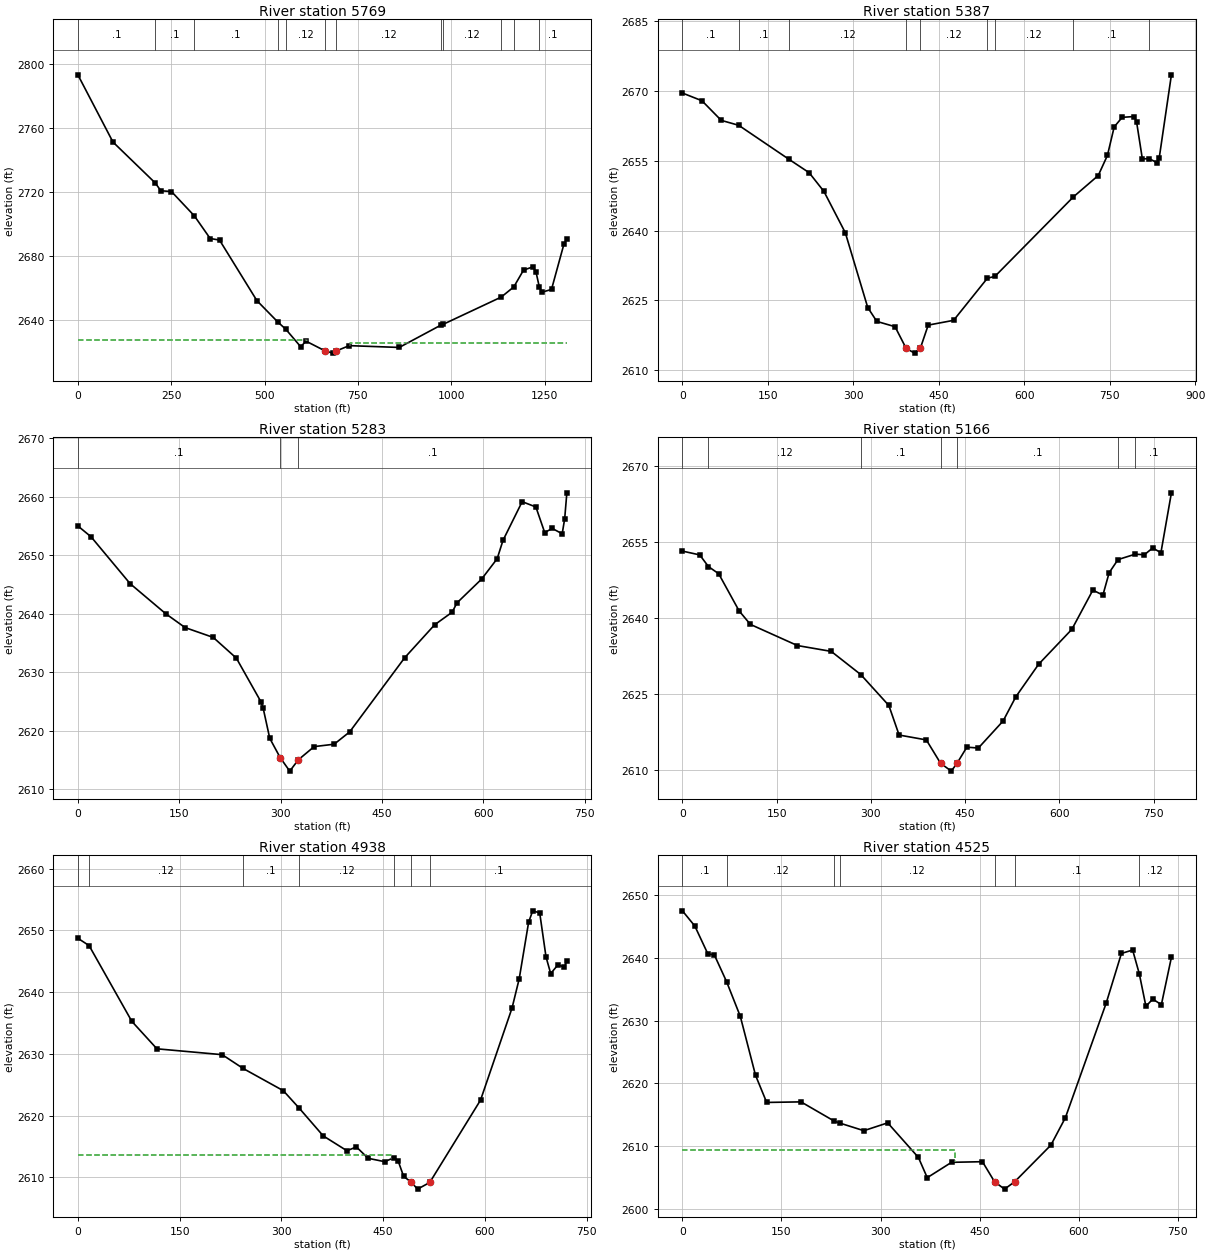
Type RM Length L Ch R = 1 ,5769    ,382.6,382.6,382.6
XS GIS Cut Line= 4
2063989.61855861400264.8641872952063476.53138441400480.900892219
2063186.23206217400615.9238327972062919.56175453400956.856757756
#Sta/Elev= 30
       0  2793.5      94  2751.4   207.62725.686   222.2 2720.88   250.7  2720.4
  312.062705.135   354.4 2690.97   379.4 2690.01   479.6 2652.04   535.42638.709
  556.972634.132   596.8 2623.19   611.1 2626.68  662.672620.514   683.2 2619.18
  691.662620.513   726.9 2623.87   860.8 2622.74  972.442636.734  979.152637.307
 1133.882654.286 1167.672660.665  1193.6 2671.16  1218.6 2673.22  1226.9 2670.19
 1236.262660.302  1243.6 2657.39  1268.6 2659.07  1301.9 2687.49  1309.7 2690.72
#Mann= 12 ,-1 , 0
       0      .1       0   207.6      .1       0  312.06      .1       0
   535.4      .1       0  556.97     .12       0  662.67    .045       0
  691.66     .12       0  972.44      .1       0  979.15     .12       0
 1133.88      .1       0 1167.67      .1       0 1236.26      .1       0
#XS Ineff= 2 , 0
          612.45 2627.39  729.71         2625.63
Permanent Ineff=
       F       F
Bank Sta=662.67,691.66
XS Rating Curve= 0 ,0
Exp/Cntr(USF)=0,0
Exp/Cntr=0.3,0.1

Type RM Length L Ch R = 1 ,5387    ,103.6,103.6,103.6
XS GIS Cut Line= 4
2063246.99238543400136.5923937462063098.46715079400403.262701387
2063020.82895996   400663.1818622062862.17700478400896.096434496
#Sta/Elev= 30
       0 2669.59    34.3 2667.93    68.1 2663.71    98.82662.648  186.552655.363
   222.4 2652.45   248.4 2648.41   285.9 2639.53   325.3 2623.42   341.2 2620.44
   373.2  2619.3   392.72614.627   407.5 2613.61  417.532614.628   431.4 2619.64
     476 2620.67  535.372629.744  548.392630.112   686.12647.221   729.9 2651.84
     746 2656.17   757.9 2662.31   771.9 2664.36   793.4 2664.54   797.3 2663.27
   807.3 2655.42   819.72655.461   833.1 2654.58     837  2655.7   858.3 2673.51
#Mann= 9 ,-1 , 0
       0      .1       0    98.8      .1       0  186.55     .12       0
   392.7    .045       0  417.53     .12       0  535.37      .1       0
  548.39     .12       0   686.1      .1       0   819.7      .1       0
Bank Sta=392.7,417.53
XS Rating Curve= 0 ,0
Exp/Cntr(USF)=0,0
Exp/Cntr=0.3,0.1

Type RM Length L Ch R = 1 ,5283    ,117,117,117
XS GIS Cut Line= 4
2063118.99855138 400228.060156842062975.82276957400381.110130498
 2062961.0114818400632.9020226462062840.05263165400864.945531096
#Sta/Elev= 30
       0 2655.03    19.5 2653.18    77.3 2645.17   129.9 2640.04   158.7 2637.66
   200.3 2635.98   234.5 2632.44   270.7 2625.02     274 2623.98   283.9 2618.74
   299.4 2615.43   313.5 2613.13   326.22615.066   349.6 2617.32   379.2 2617.73
   402.2 2619.84   483.5  2632.5   527.9 2638.14   553.8 2640.29   560.9 2641.88
   597.4 2645.95   620.4 2649.43     629 2652.56   657.4 2659.18   677.7 2658.27
   690.7 2653.91     702  2654.6   716.6 2653.69   720.3 2656.26   723.5 2660.69
#Mann= 3 , 0 , 0
       0      .1       0   299.4    .045       0   326.2      .1       0
Bank Sta=299.4,326.2
XS Rating Curve= 0 ,0
Exp/Cntr(USF)=0,0
Exp/Cntr=0.3,0.1

Type RM Length L Ch R = 1 ,5166    ,227.8,227.8,227.8
XS GIS Cut Line= 4
2063108.59387133400187.2259964622062872.30372532400406.638274901
2062838.54799018400653.0551414562062818.29454909400858.965125837
#Sta/Elev= 30
       0 2653.19    27.5 2652.44   41.412650.139    57.7 2648.73    90.2 2641.41
   108.1 2638.75     183 2634.58   236.8 2633.43  283.782628.866   328.5 2622.77
   344.8 2616.95   388.1 2615.99  410.79 2611.39   427.8 2609.84  436.992611.391
   452.6 2614.56   470.9 2614.39   510.3 2619.72   530.5 2624.48   566.9 2630.91
   619.7 2637.78   653.1  2645.5   669.1 2644.52     679 2648.92  693.122651.518
   720.52652.582   735.1 2652.47   748.3 2653.81   761.4 2652.87   778.1 2664.67
#Mann= 7 ,-1 , 0
       0      .1       0   41.41     .12       0  283.78      .1       0
  410.79    .045       0  436.99      .1       0  693.12      .1       0
   720.5      .1       0
Bank Sta=410.79,436.99
XS Rating Curve= 0 ,0
Exp/Cntr(USF)=0,0
Exp/Cntr=0.3,0.1

Type RM Length L Ch R = 1 ,4938    ,413.9,413.9,413.9
XS GIS Cut Line= 3
2063071.46256268400193.9771434912062747.40750529400345.877951641
2062490.86391819400602.421538739
#Sta/Elev= 30
       0 2648.71   16.532647.525    79.5 2635.27   116.5 2630.82   212.7 2629.87
  243.672627.633   302.8 2624.04  326.072621.233   361.6 2616.73   396.6 2614.32
   410.5 2614.94   427.8  2613.1   452.3 2612.55  465.76  2613.2   471.9 2612.72
   480.1 2610.19  491.672609.193   500.7 2608.11  518.672609.193   593.5 2622.52
   639.9 2637.41   650.5 2642.16   664.4 2651.33   670.4 2653.15   680.7 2652.82
     690 2645.69   696.9    2643   707.5  2644.4   716.8 2644.06   720.7 2644.97
#Mann= 7 ,-1 , 0
       0      .1       0   16.53     .12       0  243.67      .1       0
  326.07     .12       0  465.76      .1       0  491.67    .045       0
  518.67      .1       0
#XS Ineff= 2 , 0
          462.25 2613.64
Permanent Ineff=
       F       F
Bank Sta=491.67,518.67
XS Rating Curve= 0 ,0
Exp/Cntr(USF)=0,0
Exp/Cntr=0.3,0.1

Type RM Length L Ch R = 1 ,4525    ,210.7,210.7,210.7
XS GIS Cut Line= 3
2063091.71600376400156.8458348322062764.28537286400163.596981861
2062359.21655113400082.583217515
#Sta/Elev= 30
       0 2647.54    18.8 2645.11    38.5 2640.67    48.4 2640.49   66.782636.255
    87.7 2630.68   110.7 2621.29   127.6 2616.95   179.6 2617.04  230.08 2613.96
  238.122613.662   274.8 2612.44   310.9 2613.69   357.4 2608.17   370.8 2604.94
   407.6 2607.39   454.4 2607.49  472.722604.291   487.9 2603.11  503.252604.292
   558.1 2610.14     580 2614.51   641.8  2632.8   664.9 2640.74   681.9 2641.28
  691.962637.492     702  2632.3   712.3 2633.45   725.4 2632.56   740.6 2640.12
#Mann= 7 ,-1 , 0
       0      .1       0   66.78     .12       0  230.08      .1       0
  238.12     .12       0  472.72    .045       0  503.25      .1       0
  691.96     .12       0
#XS Ineff= 2 , 0
          412.81 2609.36
Permanent Ineff=
       F       F
Bank Sta=472.72,503.25
XS Rating Curve= 0 ,0
Exp/Cntr(USF)=0,0
Exp/Cntr=0.3,0.1

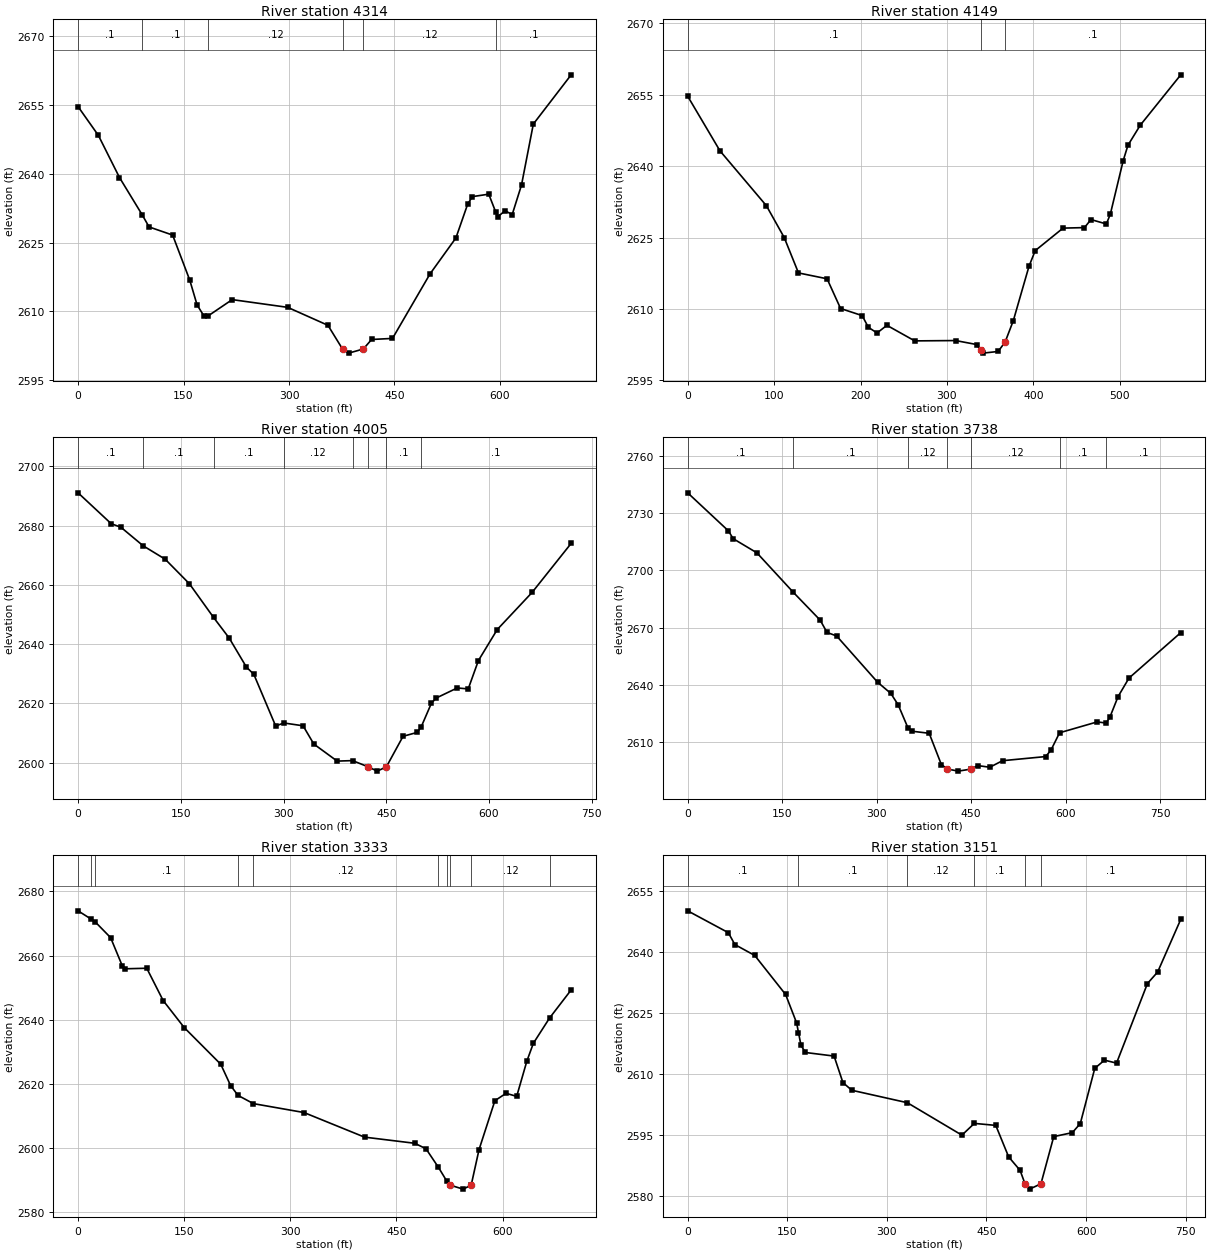
Type RM Length L Ch R = 1 ,4314    ,165,165,165
XS GIS Cut Line= 4
2062943.19076913399792.2838952722062690.02275554399900.302247734
2062487.48834468399994.8183061392062288.32950732400031.949614798
#Sta/Elev= 30
       0 2654.56    28.9  2648.3    58.9 2639.14   90.95 2631.09     101 2628.39
   134.5 2626.62   158.9  2616.8   169.3 2611.41   178.9 2609.06  185.492609.089
   219.2 2612.58   298.1  2610.9   355.4 2606.99  376.112601.831   384.8 2600.94
  405.692601.833   417.5 2603.91   447.2 2604.14   500.6 2618.18   537.4    2626
     554  2633.3   560.7 2634.98   584.1 2635.52   593.9 2631.67   597.4 2630.66
   607.4 2631.93   617.4 2631.06   630.7 2637.52   647.5 2650.77   701.3 2661.48
#Mann= 6 ,-1 , 0
       0      .1       0   90.95      .1       0  185.49     .12       0
  376.11    .045       0  405.69     .12       0   593.9      .1       0
Bank Sta=376.11,405.69
XS Rating Curve= 0 ,0
Exp/Cntr(USF)=0,0
Exp/Cntr=0.3,0.1

Type RM Length L Ch R = 1 ,4149    ,144.3,144.3,144.3
XS GIS Cut Line= 3
2062785.74457648399702.2594408842062363.62287494399884.931990089
2062262.41240848399929.365853409
#Sta/Elev= 30
       0 2654.68    37.4  2643.2    91.1 2631.68   111.7    2625   128.2 2617.57
   161.3 2616.34   176.9  2610.1   201.9 2608.61     209 2606.16   219.1 2604.96
   230.5 2606.57   262.7  2603.3     310 2603.37   334.2 2602.54   338.82601.411
   341.8 2600.73   359.2 2601.08   367.32603.065   376.8 2607.57   394.9 2618.96
   402.1 2622.25   434.3 2626.98   459.1 2627.09   466.6 2628.78   484.4 2627.85
     489  2629.9   503.9 2641.15   509.4 2644.38   523.6 2648.58   570.5 2659.17
#Mann= 3 , 0 , 0
       0      .1       0   338.8    .045       0   367.3      .1       0
Bank Sta=338.8,367.3
XS Rating Curve= 0 ,0
Exp/Cntr(USF)=0,0
Exp/Cntr=0.3,0.1

Type RM Length L Ch R = 1 ,4005    ,266.4,266.4,266.4
XS GIS Cut Line= 3
2062814.91897558399552.6181757462062551.62424145399670.763248752
2062139.80427269399799.035042301
#Sta/Elev= 30
       0 2691.03    48.4 2680.61    62.5 2679.43   95.062673.163   127.2 2668.64
   162.6 2660.35  197.87 2648.99   220.7 2642.03   245.8 2632.25   256.6 2629.83
   288.5 2612.39  300.382613.417   328.5 2612.47   344.2 2606.31   378.3 2600.56
  400.712600.729  423.782598.609   436.7 2597.18  450.082598.607   474.5 2608.93
   495.2 2610.24  501.042612.141   515.8 2620.04   522.7 2621.81   553.6 2625.23
   569.6  2624.9   584.5 2634.47     612 2644.93   662.9 2657.45   719.9 2673.98
#Mann= 8 ,-1 , 0
       0      .1       0   95.06      .1       0  197.87      .1       0
  300.38     .12       0  400.71      .1       0  423.78    .045       0
  450.08      .1       0  501.04      .1       0
Bank Sta=423.78,450.08
XS Rating Curve= 0 ,0
Exp/Cntr(USF)=0,0
Exp/Cntr=0.3,0.1

Type RM Length L Ch R = 1 ,3738    ,404.8,404.8,404.8
XS GIS Cut Line= 4
2062737.28078475399265.694427018 2062423.3524479399417.595235168
2062214.06689001399545.8670287172062079.04394943399677.514395781
#Sta/Elev= 30
       0 2740.57    64.7 2720.64    72.2 2716.57   109.9 2709.14  167.48 2688.55
   210.3 2673.92   221.2 2667.48   236.5  2665.6   301.4 2641.44   322.5 2635.53
   334.2 2629.54  349.512617.645   356.6 2615.72   383.4 2614.66   402.7  2598.3
  412.372595.929   429.6 2594.84  450.112595.929   460.4 2597.75   479.6 2596.87
   499.8  2600.3   568.2 2602.46   576.6 2605.74   590.4 2614.92   650.2 2620.62
  664.292620.018   670.3 2623.12   683.3 2633.88   700.6 2643.57   782.8 2667.35
#Mann= 7 ,-1 , 0
       0      .1       0  167.48      .1       0  349.51     .12       0
  412.37    .045       0  450.11     .12       0   590.4      .1       0
  664.29      .1       0
Bank Sta=412.37,450.11
XS Rating Curve= 0 ,0
Exp/Cntr(USF)=0,0
Exp/Cntr=0.3,0.1

Type RM Length L Ch R = 1 ,3333    ,182.4,182.4,182.4
XS GIS Cut Line= 3
2062453.73260953399042.9065750652062190.43787541399275.821147562
2061998.03018508 399562.74489629
#Sta/Elev= 30
       0 2673.95   18.472671.366   24.23  2670.5      46 2665.59    62.5  2656.8
    66.9 2655.88    97.1 2656.05   120.3 2645.97   150.1 2637.54   201.7 2626.12
   215.6 2619.48   226.1 2616.41  247.842613.844   319.3 2611.07   404.9  2603.4
     476 2601.48   491.8 2599.77  509.452593.961  521.032589.749  525.992588.428
   544.3 2587.19  555.692588.429   566.8 2599.52   589.2 2614.76     605 2617.06
     620 2616.11   634.4 2627.11   643.6 2632.67  666.51 2640.54     697 2649.29
#Mann= 10 ,-1 , 0
       0      .1       0   18.47      .1       0   24.23      .1       0
   226.1      .1       0  247.84     .12       0  509.45      .1       0
  521.03     .12       0  525.99    .045       0  555.69     .12       0
  666.51      .1       0
Bank Sta=525.99,555.69
XS Rating Curve= 0 ,0
Exp/Cntr(USF)=0,0
Exp/Cntr=0.3,0.1

Type RM Length L Ch R = 1 ,3151    ,305.7,305.7,305.7
XS GIS Cut Line= 3
 2062072.2928024398816.7431495972062014.90805265399188.056236186
2061856.25609748399518.862440602
#Sta/Elev= 30
       0 2650.23    61.2 2644.86    71.1 2641.93     101 2639.26   147.5 2629.66
   164.1 2622.66  166.892620.293   170.7 2617.14   177.4  2615.4   220.5 2614.52
   233.8 2608.01   247.1 2606.12  330.812603.056     413 2595.08  431.72 2597.97
     464 2597.48   483.4 2589.74   500.6 2586.43  508.042583.117   514.9 2581.81
  532.022583.118   551.3 2594.72   579.3  2595.7   591.3 2597.93   613.1  2611.5
   627.7 2613.52   645.9 2612.79   692.4 2632.35   707.8 2635.19   742.6 2648.14
#Mann= 6 ,-1 , 0
       0      .1       0  166.89      .1       0  330.81     .12       0
  431.72      .1       0  508.04    .045       0  532.02      .1       0
Bank Sta=508.04,532.02
XS Rating Curve= 0 ,0
Exp/Cntr(USF)=0,0
Exp/Cntr=0.3,0.1

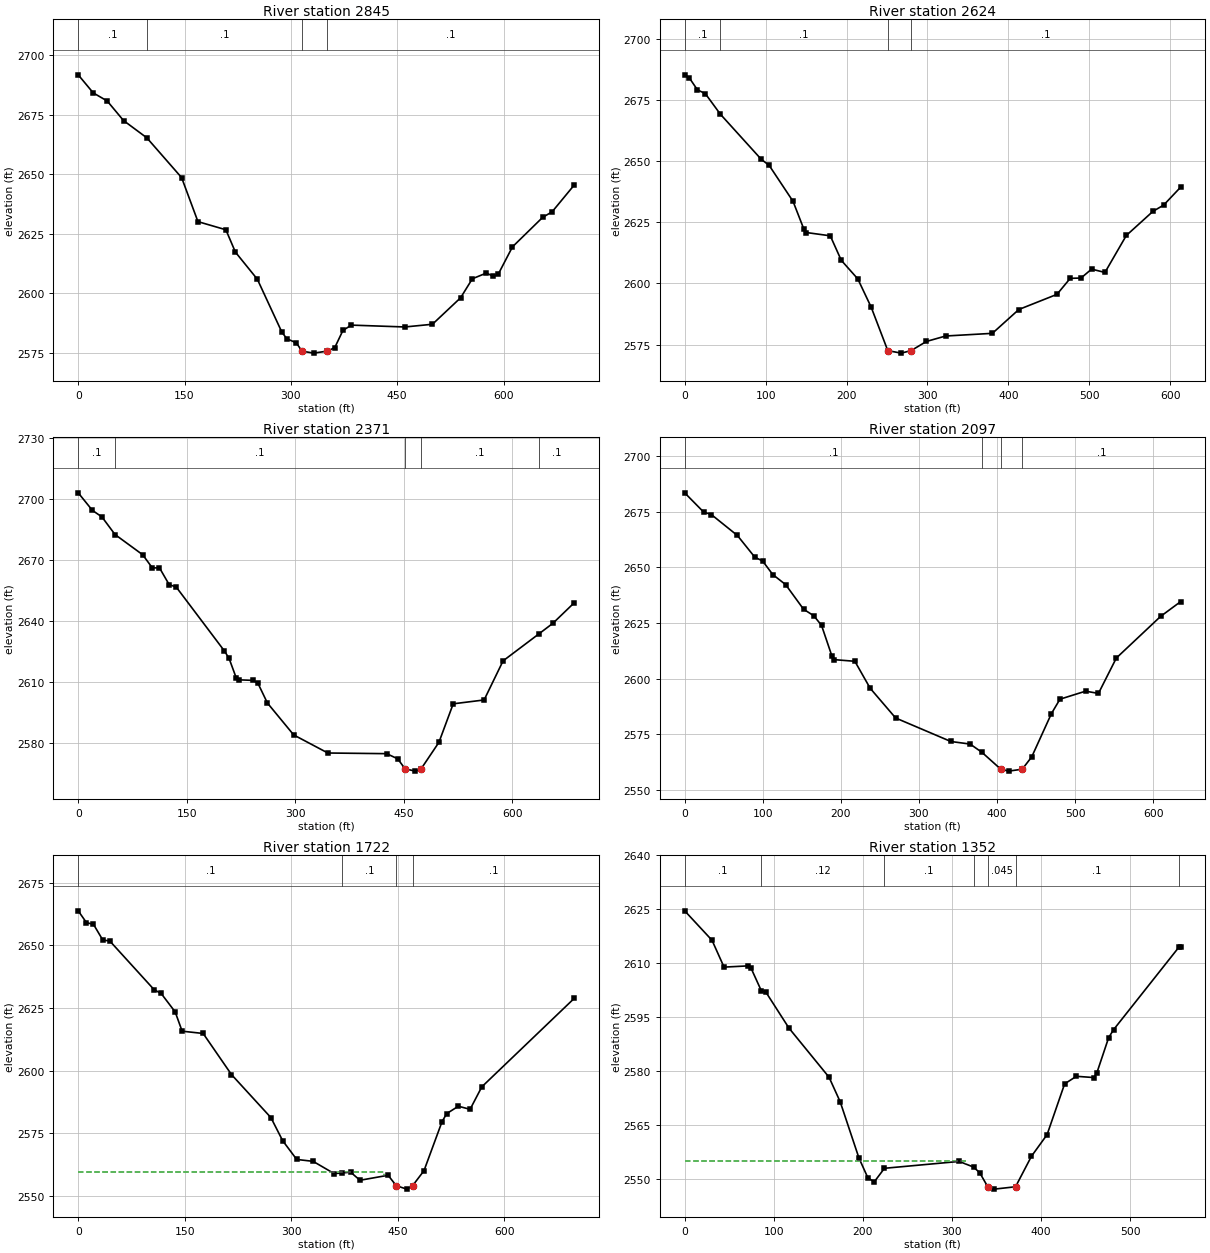
Type RM Length L Ch R = 1 ,2845    ,220.9,220.9,220.9
XS GIS Cut Line= 4
2061751.61331853398813.3675760822061758.36446556399029.404281007
2061680.72627472399269.0700005332061650.34611309399498.608999515
#Sta/Elev= 30
       0 2691.74    21.2 2684.15    40.9 2680.75    63.9 2672.54   96.832665.261
   145.9 2648.54   168.9 2630.06   208.3 2626.64   221.7 2617.27   252.7 2605.85
   287.2 2583.68   294.1 2580.91   307.9 2579.06  315.552575.666     332 2574.81
   351.52575.666   361.9 2577.13   373.4 2584.33   385.3 2586.58   460.8  2585.8
   499.7 2586.94   539.4 2598.06     556 2606.05   575.8 2608.46   585.7 2607.06
   592.4  2607.9   612.6 2619.47   655.2 2631.86   668.5 2634.18   699.6  2645.4
#Mann= 4 ,-1 , 0
       0      .1       0   96.83      .1       0  315.55    .045       0
   351.5      .1       0
Bank Sta=315.55,351.5
XS Rating Curve= 0 ,0
Exp/Cntr(USF)=0,0
Exp/Cntr=0.3,0.1

Type RM Length L Ch R = 1 ,2624    ,253.6,253.6,253.6
XS GIS Cut Line= 4
 2061488.3185844398891.0057669152061495.06973143 399069.91116318
2061552.45448117399285.9478681052061532.20104009399495.233426001
#Sta/Elev= 30
       0  2685.4     5.9 2684.06    15.7 2679.28    25.6 2677.66   44.082669.288
    94.5 2650.86   104.4 2648.32   133.9  2633.6   147.1 2622.37   150.3 2620.84
   179.9  2619.5   193.5 2609.46   213.9 2601.86   230.5 2590.24  250.982572.489
   267.5 2571.47  279.74 2572.49   298.7 2576.25   322.5 2578.48   380.2 2579.57
   412.9 2589.33     460 2595.53   476.4 2602.09   489.7 2602.21   502.8 2605.86
   519.3  2604.5   545.7 2619.63   578.6 2629.51   591.8 2632.06   612.8  2639.4
#Mann= 4 ,-1 , 0
       0      .1       0   44.08      .1       0  250.98    .045       0
  279.74      .1       0
Bank Sta=250.98,279.74
XS Rating Curve= 0 ,0
Exp/Cntr(USF)=0,0
Exp/Cntr=0.3,0.1

Type RM Length L Ch R = 1 ,2371    ,273.9,273.9,273.9
XS GIS Cut Line= 3
2061295.91089408398877.5034728572061343.16892328399215.060824302
2061349.92007031399559.369322775
#Sta/Elev= 30
       0 2702.94    19.6 2694.32    32.8 2691.08   50.822682.454    89.1  2672.5
   102.4 2666.04   112.3 2666.05   125.6 2657.86   135.5 2656.59   202.1 2625.16
   208.4 2621.58   218.3 2611.98   221.7 2611.02   241.5 2610.75   248.2  2609.4
   261.4 2599.62   297.7 2583.94   344.9 2575.05   426.2 2574.72   441.4 2572.19
   451.62567.279   465.6 2566.14  473.782567.281   498.4 2580.32   518.1 2599.23
   560.8 2601.12     587 2620.34   636.62633.631   655.9 2638.83   685.2 2648.86
#Mann= 5 ,-1 , 0
       0      .1       0   50.82      .1       0   451.6    .045       0
  473.78      .1       0   636.6      .1       0
Bank Sta=451.6,473.78
XS Rating Curve= 0 ,0
Exp/Cntr(USF)=0,0
Exp/Cntr=0.3,0.1

Type RM Length L Ch R = 1 ,2097    ,375.2,375.2,375.2
XS GIS Cut Line= 3
2061086.62533618398938.2637961172061079.87418915399275.821147562
2061066.37189509399572.871616833
#Sta/Elev= 30
       0 2683.56    24.2 2674.93    34.1  2673.8    67.5 2664.37    89.9 2654.57
    99.7 2652.94   112.8 2646.81   129.3 2642.26   152.2 2631.21   165.3 2628.27
   175.2 2623.97   188.3 2610.38   191.6 2608.53   217.9 2607.79   237.5 2595.66
   270.1 2582.29   340.8 2571.72   365.5 2570.56  380.642566.836  404.752559.259
   414.8 2558.39   432.22559.258   444.4 2564.82   469.6 2584.28   480.5 2590.74
   513.3 2594.35   529.8 2593.35   552.7 2609.26   609.4 2627.99     635 2634.62
#Mann= 4 ,-1 , 0
       0      .1       0  380.64      .1       0  404.75    .045       0
   432.2      .1       0
Bank Sta=404.75,432.2
XS Rating Curve= 0 ,0
Exp/Cntr(USF)=0,0
Exp/Cntr=0.3,0.1

Type RM Length L Ch R = 1 ,1722    ,370,370,370
XS GIS Cut Line= 3
2060738.94126419398921.3859285452060725.43897014399157.676074556
2060678.18094093399616.754072521
#Sta/Elev= 30
       0 2663.74    11.6 2659.03    21.5 2658.35    34.6 2652.09    44.5  2651.7
   106.9 2632.28   116.8 2630.77   136.5 2623.43   146.3 2615.74   175.9 2614.83
   215.8 2598.43   271.3 2581.27   287.8 2572.08   307.6 2564.59   330.7 2563.83
   360.4 2558.93  371.962559.217   383.5 2559.52   396.7 2556.28   436.3 2558.28
  447.722554.121   462.6 2552.75  470.75 2554.12   486.8 2560.11   512.1 2579.58
   518.7 2582.86   535.2 2585.81   551.7 2584.58   568.2 2593.54   698.2  2628.8
#Mann= 4 ,-1 , 0
       0      .1       0  371.96      .1       0  447.72    .045       0
  470.75      .1       0
#XS Ineff= 2 , 0
          430.62  2559.7
Permanent Ineff=
       F       F
Bank Sta=447.72,470.75
XS Rating Curve= 0 ,0
Exp/Cntr(USF)=0,0
Exp/Cntr=0.3,0.1

Type RM Length L Ch R = 1 ,1352    ,248.1,248.1,248.1
XS GIS Cut Line= 3
2060398.00833923398968.6439577472060347.37473652399188.056236186
2060323.74572192399518.862440602
#Sta/Elev= 30
       0 2624.53    30.7 2616.34    44.2 2608.88    71.1 2609.22    74.5  2608.6
   85.972602.348    91.3 2601.88   117.1 2591.92   162.1 2578.26   174.6 2571.43
   195.7 2555.78   205.8 2550.23   212.9 2549.19  224.292552.942   308.2 2554.85
  324.392553.279   331.3 2551.69  340.282547.806   347.7 2547.15   371.52547.809
   389.4 2556.31   406.9  2562.3   426.6 2576.42   439.8 2578.52   459.5 2578.17
   462.8 2579.49     476 2589.25   481.5 2591.47  554.622614.335  556.83 2614.58
#Mann= 7 ,-1 , 0
       0      .1       0   85.97     .12       0  224.29      .1       0
  324.39      .1       0  340.28    .045       0   371.5      .1       0
  554.62      .1       0
#XS Ineff= 2 , 0
          315.79 2555.08
Permanent Ineff=
       F       F
Bank Sta=340.28,371.5
XS Rating Curve= 0 ,0
Exp/Cntr(USF)=0,0
Exp/Cntr=0.3,0.1

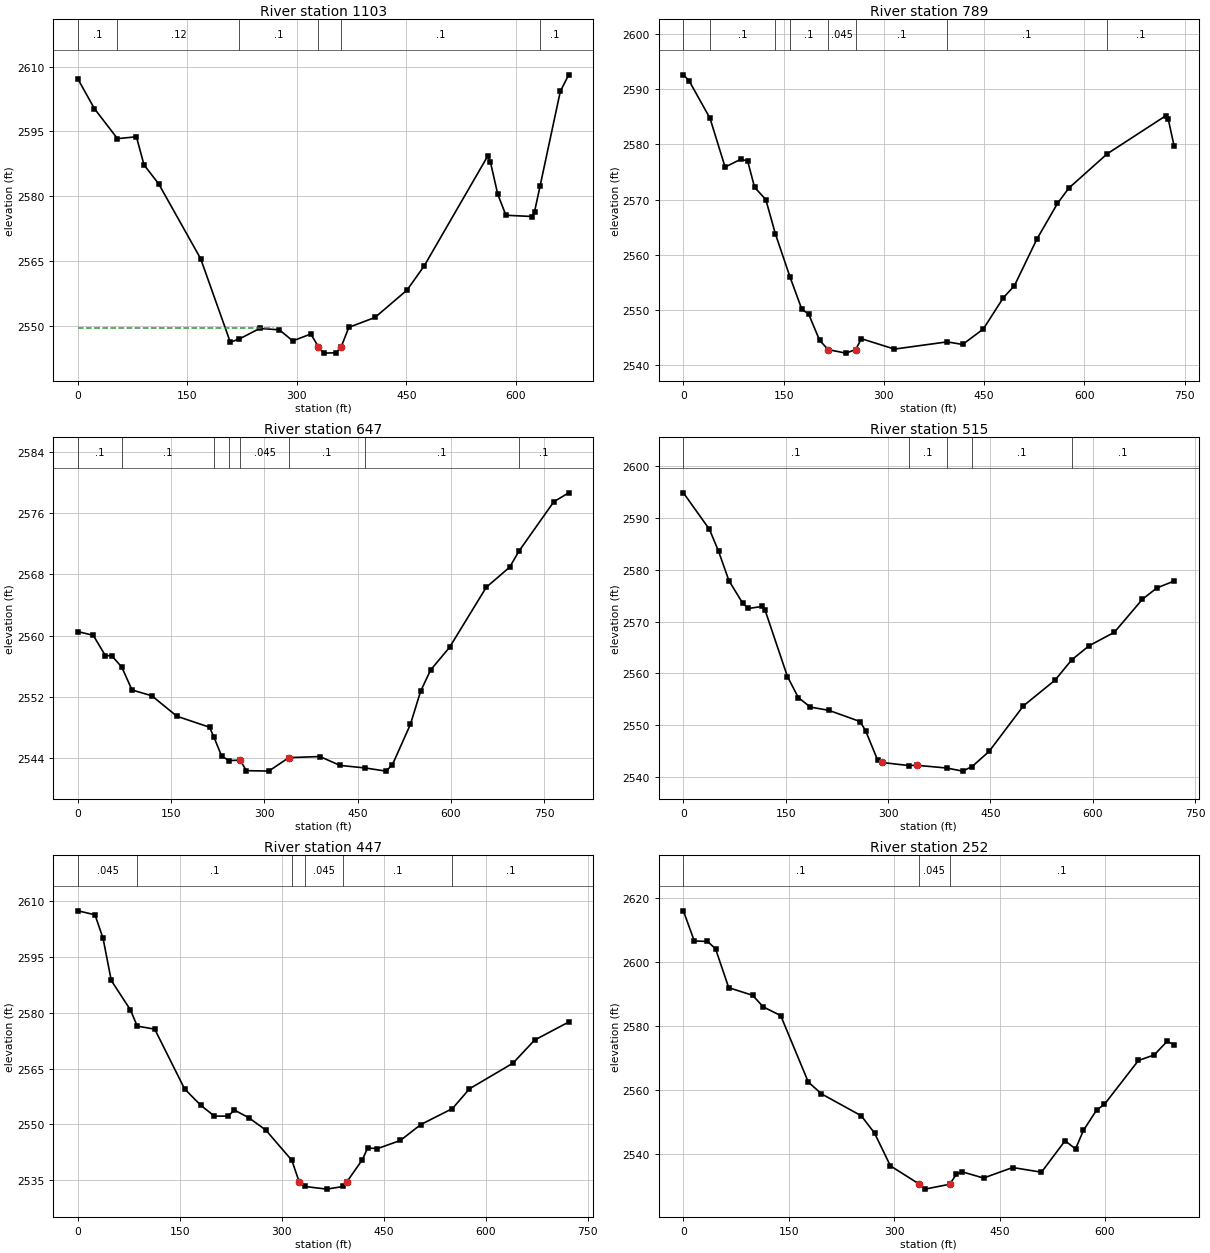
Type RM Length L Ch R = 1 ,1103    ,314,314,314
XS GIS Cut Line= 4
2060185.34720782398907.8836344872060134.71360511399107.042471839
2060070.57770833399390.5906470532060107.70901699 399562.74489629
#Sta/Elev= 30
       0 2607.09    22.5 2600.26   54.172593.293    80.1 2593.73    90.5 2587.21
   110.5 2582.85   168.1 2565.48   208.7 2546.15  221.072546.888     249 2549.33
   275.9 2549.01   294.3 2546.44     319 2548.04  329.422545.073   336.5 2543.61
   353.3 2543.69  360.642545.074   371.1 2549.58   407.1 2551.89   450.9 2558.23
   474.4 2563.83   561.4 2589.27   565.1 2587.85   575.1 2580.41   586.3 2575.55
   622.2 2575.26   625.5 2576.37  633.032582.267   660.8 2604.24  672.32 2608.08
#Mann= 6 ,-1 , 0
       0      .1       0   54.17     .12       0  221.07      .1       0
  329.42    .045       0  360.64      .1       0  633.03      .1       0
#XS Ineff= 2 , 0
           267.8 2549.41
Permanent Ineff=
       F       F
Bank Sta=329.42,360.64
XS Rating Curve= 0 ,0
Exp/Cntr(USF)=0,0
Exp/Cntr=0.3,0.1

Type RM Length L Ch R = 1 ,789     ,142,142,142
XS GIS Cut Line= 4
2059938.93034127398809.9920025682059895.04788558398988.897398834
2059874.79444449399231.9386918742059949.05706181399528.989161145
#Sta/Elev= 30
       0  2592.6     8.4 2591.55   39.832584.732    62.4  2575.9    86.1 2577.33
    96.2 2576.98   106.5 2572.24   123.3 2570.02  137.792563.755  159.612555.969
   177.3 2550.13   187.4  2549.3   203.8 2544.54  216.642542.856     243 2542.22
  257.672542.856   266.4 2544.83   315.7 2542.95  394.582544.257   417.8 2543.79
   448.8 2546.59   478.6 2552.23   495.3 2554.43   529.1 2562.91   559.7 2569.31
   576.5 2572.07  634.172578.306   721.9  2585.2   725.3 2584.66  734.28 2579.68
#Mann= 8 ,-1 , 0
       0      .1       0   39.83      .1       0  137.79     .12       0
  159.61      .1       0  216.64    .045       0  257.67      .1       0
  394.58      .1       0  634.17      .1       0
Bank Sta=216.64,257.67
XS Rating Curve= 0 ,0
Exp/Cntr(USF)=0,0
Exp/Cntr=0.3,0.1

Type RM Length L Ch R = 1 ,647     ,132.9,132.9,132.9
XS GIS Cut Line= 4
2059743.58285836398750.9111789562059746.48875652398967.400592028
2059759.56529825399159.1898707232059890.33071554399516.615344654
#Sta/Elev= 30
       0 2560.51    24.6 2560.03    44.3 2557.34    54.1 2557.38    70.5 2555.86
    86.9 2552.87   118.8 2552.11   159.1 2549.43   211.6 2547.99   218.7 2546.69
   231.3 2544.17   243.4 2543.63   260.9 2543.67   270.8  2542.3     307 2542.25
   339.2 2544.01   389.2 2544.15   421.4 2542.99   461.3 2542.66   495.6 2542.24
   505.8 2543.09   534.7 2548.37   551.1  2552.7   567.2 2555.49   597.6 2558.45
   656.7 2566.32   694.3 2568.95   709.4 2571.07   765.3 2577.52   789.3 2578.69
#Mann= 8 ,-1 , 0
       0      .1       0    70.5      .1       0   218.7     .12       0
   243.4      .1       0   260.9    .045       0   339.2      .1       0
   461.3      .1       0   709.4      .1       0
Bank Sta=260.9,339.2
XS Rating Curve= 0 ,0
Exp/Cntr(USF)=0,0
Exp/Cntr=0.3,0.1

Type RM Length L Ch R = 1 ,515     ,67.8,67.8,67.8
XS GIS Cut Line= 4
2059501.40058345398918.6282006892059644.98101164399113.991734124
2059781.50010729399275.2254936452059883.25432478399520.560139323
#Sta/Elev= 30
       0 2594.89    38.2 2587.83    51.6 2583.59    66.7 2577.93      87 2573.56
    95.2 2572.55   114.9 2572.94   119.6 2572.28   152.5 2559.41   168.5 2555.34
   186.1 2553.51   213.5 2552.87   258.9 2550.72     267 2548.96   284.7 2543.27
   290.5 2542.82   330.1 2542.22   341.8 2542.27     386 2541.74   409.3 2541.14
   423.2 2542.03   448.1 2544.95   498.4 2553.75   544.9 2558.73     569 2562.61
   594.7 2565.36   631.7 2567.96   672.8 2574.34   694.1 2576.53   719.3 2577.85
#Mann= 5 ,-1 , 0
       0      .1       0   330.1      .1       0     386    .045       0
   423.2      .1       0     569      .1       0
Bank Sta=290.5,341.8
XS Rating Curve= 0 ,0
Exp/Cntr(USF)=0,0
Exp/Cntr=0.3,0.1

Type RM Length L Ch R = 1 ,447     ,194.7,194.7,194.7
XS GIS Cut Line= 4
2059449.47218167398951.7660901752059587.87069577399150.924927527
2059776.90281257399353.4593383942059878.17001801399528.989161145
#Sta/Elev= 30
       0 2607.44    25.1 2606.37      37    2600      49 2588.71    77.1 2580.83
   87.242576.432     113 2575.61   156.9 2559.55   180.9  2555.1   200.9 2552.22
   220.9 2552.22   230.3 2553.84   251.4 2551.79   276.5 2548.46  314.832540.306
   325.6 2534.49  334.162533.287   366.2 2532.58  390.042533.287   395.3 2534.41
   418.5  2540.5   426.4 2543.65   440.8 2543.48   474.5 2545.67   504.4 2549.94
  551.152554.254   576.2 2559.57   640.2 2566.47     672 2572.67  722.22 2577.53
#Mann= 6 ,-1 , 0
       0    .045       0   87.24      .1       0  314.83      .1       0
  334.16    .045       0  390.04      .1       0  551.15      .1       0
Bank Sta=325.6,395.3
XS Rating Curve= 0 ,0
Exp/Cntr(USF)=0,0
Exp/Cntr=0.3,0.1

Type RM Length L Ch R = 1 ,252     ,249,249,249
XS GIS Cut Line= 4
2059263.51035047399226.8344973712059522.97256422399374.057438879
2059659.99193552399452.7706947352059872.80925691399567.925272746
#Sta/Elev= 30
       0 2615.94    15.5  2606.5    34.3 2606.37    45.7 2604.09    64.5 2591.91
    98.5 2589.52   113.6 2585.91   138.5 2583.16   177.7 2562.41   196.5  2558.7
   253.1 2551.85     272 2546.43   294.6 2536.18   334.9 2530.58   343.8 2528.91
     379 2530.44   388.6 2533.63   396.8 2534.31   427.1 2532.38   468.5 2535.67
   509.5  2534.2   543.1 2544.03     558 2541.49   569.2 2547.25   587.9 2553.61
     599  2555.4   647.5 2569.14   669.9 2570.87   688.6 2575.19698.3147 2573.93
#Mann= 3 , 0 , 0
       0      .1       0   334.9    .045       0     379      .1       0
Bank Sta=334.9,379
XS Rating Curve= 0 ,0
Exp/Cntr(USF)=0,0
Exp/Cntr=0.3,0.1