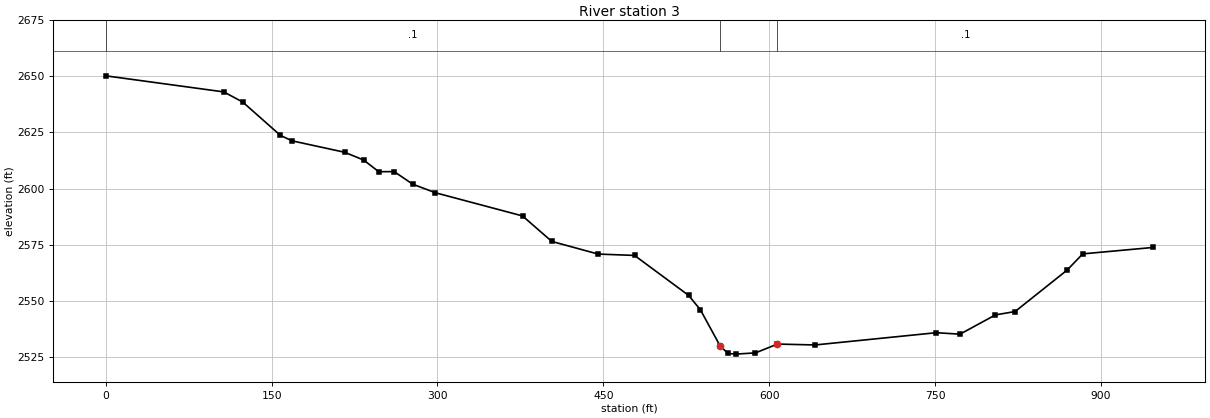
HEC-RAS study HOMINYCK.prj: HOMINYCK

--- HOMINYCK.g01 (geometry) --- (continued)

Type RM Length L Ch R = 1 ,3       ,3,3,3
XS GIS Cut Line= 4
2058977.81038477399804.0650403142059403.44502755399678.706892099
2059754.73937313399531.4839505912059865.52099248399583.959454495
#Sta/Elev= 30
       0 2650.27   106.7  2643.1   123.8 2638.59     158 2623.68   168.5 2621.27
   216.1 2616.16   233.2 2612.71   246.9 2607.49   260.8 2607.55   277.7 2601.91
   298.2  2598.1   376.9 2587.77   403.4 2576.39   445.3 2570.76   478.2 2570.15
   527.1 2552.34   537.8 2545.89   555.6 2529.81   562.7 2526.43   569.8 2526.12
   587.6 2526.68   607.5 2530.61   641.5 2530.21   751.2 2535.68   772.6 2535.02
   804.6 2543.61   822.4 2545.12   869.5 2563.62   883.6 2570.84947.1894 2573.71
#Mann= 3 , 0 , 0
       0      .1       0   555.6    .045       0   607.5      .1       0
Bank Sta=555.6,607.5
XS Rating Curve= 0 ,0
Exp/Cntr(USF)=0,0
Exp/Cntr=0.3,0.1
Stream Node=ANGLINSCK       ,Main            , 0 , 0 ,Upstream end
Stream Node=ANGLINSCK       ,Main            , 0 , 1 ,Downstream end
Stream Node=GRBRRVTR1       ,Main            , 0 , 0 ,Upstream end
Stream Node=GRBRRVTR1       ,Main            , 0 , 1 ,Downstream end
Stream Node=GRBRRVTR2       ,Main            , 0 , 0 ,Upstream end
Stream Node=GRBRRVTR2       ,Main            , 0 , 1 ,Downstream end
Stream Node=GRBRRVTR4       ,Main            , 0 , 0 ,Upstream end
Stream Node=GRBRRVTR4       ,Main            , 0 , 1 ,Downstream end
Stream Node=HOMINYCK        ,Main            , 0 , 0 ,Upstream end
Stream Node=HOMINYCK        ,Main            , 0 , 1 ,Downstream end
Stream Node=HOWARDCK        ,Main            , 0 , 0 ,Upstream end
Stream Node=HOWARDCK        ,Main            , 0 , 1 ,Downstream end
Stream Node=JERCHODFT       ,Main            , 0 , 0 ,Upstream end
Stream Node=JERCHODFT       ,Main            , 0 , 1 ,Downstream end
Stream Node=JERCHODFTT1     ,Main            , 0 , 0 ,Upstream end
Stream Node=JERCHODFTT1     ,Main            , 0 , 1 ,Downstream end
Stream Node=LITTLECK2       ,Main            , 0 , 0 ,Upstream end
Stream Node=LITTLECK2       ,Main            , 0 , 1 ,Downstream end
Stream Node=SLPHRLCKRN      ,Main            , 0 , 0 ,Upstream end
Stream Node=SLPHRLCKRN      ,Main            , 0 , 1 ,Downstream end
Stream Node=SLSHLCKRN       ,Main            , 0 , 0 ,Upstream end
Stream Node=SLSHLCKRN       ,Main            , 0 , 1 ,Downstream end
Stream Node=YOUNGSCK        ,Main            , 0 , 0 ,Upstream end
Stream Node=YOUNGSCK        ,Main            , 0 , 1 ,Downstream end
LCMann Table=0

Chan Stop Cuts=-1
Use User Specified Reach Order=0
Composite Channel Slope=5